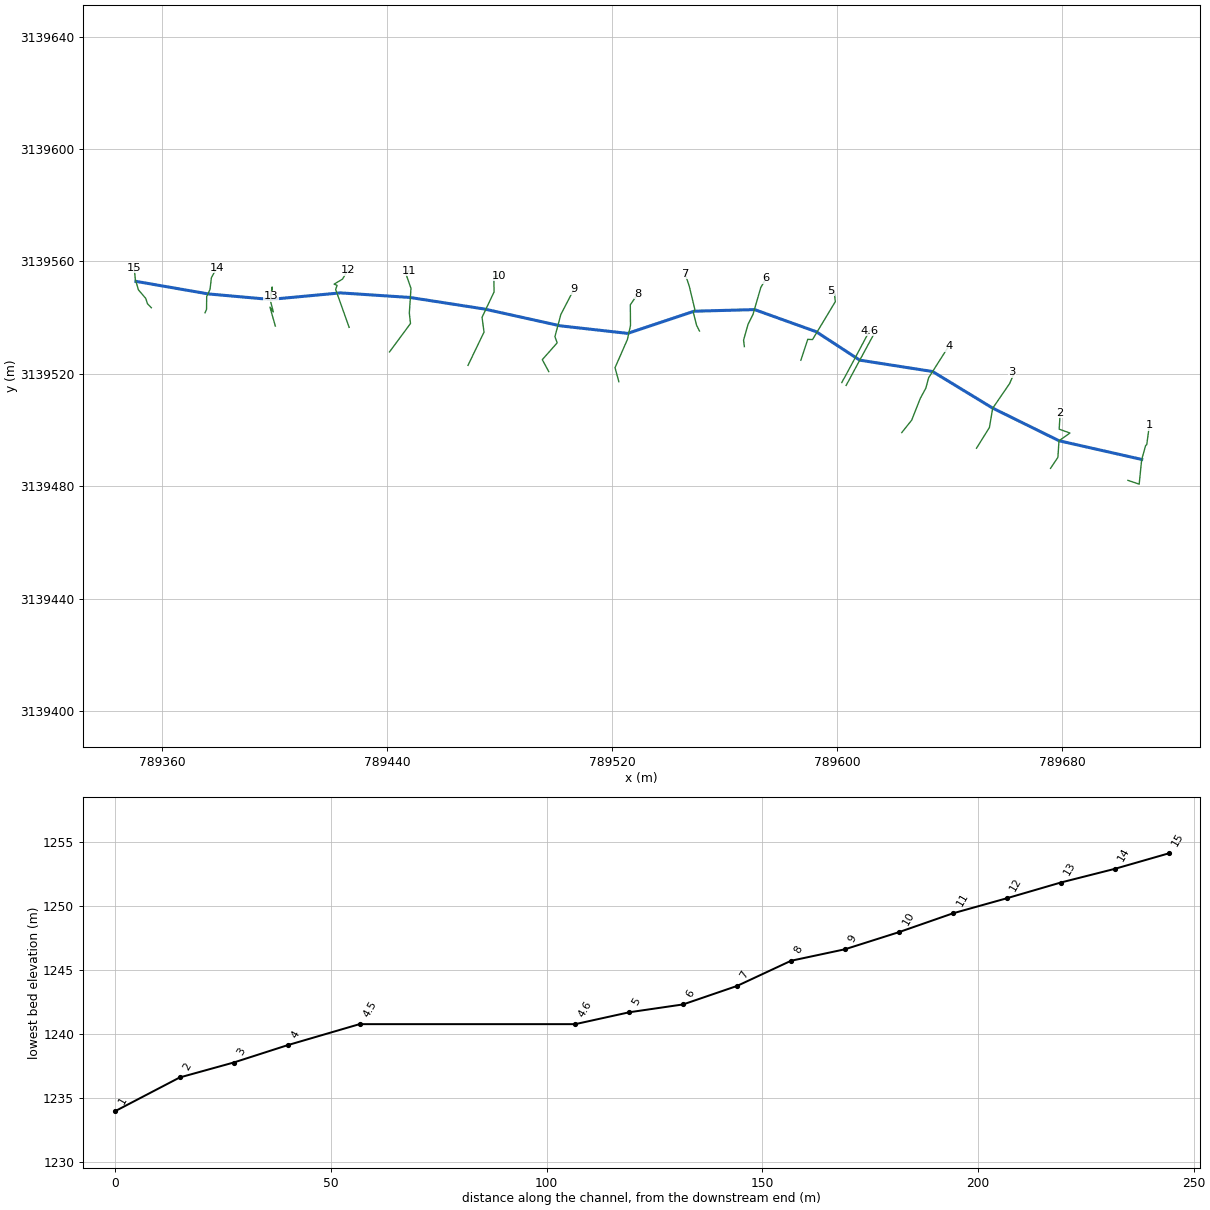
--- RiverDhiprangMode.prj (project) ---

Proj Title=River Dhiprang Model
Current Plan=p03
Current HD=h01
Default Exp/Contr=0.3,0.1
SI Units
Geom File=g02
Geom File=g03
Flow File=f01
Unsteady File=u01
Plan File=p03
HD File=h01
Y Axis Title=Elevation
X Axis Title(PF)=Main Channel Distance
X Axis Title(XS)=Station
BEGIN DESCRIPTION:
END DESCRIPTION:
DSS File=dss
DSS Export Rating Curves= 0
DSS Export Rating Curve Sorted= 0
DSS Export Volume Flow Curves= 0
DXF OffsetX= 0
DXF OffsetY= 0
DXF ScaleX= 1
DXF ScaleY= 10

--- RiverDhiprangMode.p03 (plan) ---

Plan Title=Steady Flow Analysis with bridge
Program Version=6.41
Short Identifier=Steady bridge
Geom File=g03
Flow File=f01
Subcritical Flow
K Sum by GR= 0
Std Step Tol= 0.003
Critical Tol= 0.003
Num of Std Step Trials= 20
Max Error Tol= 0.1
Flow Tol Ratio= 0.001
Split Flow NTrial= 30
Split Flow Tol= 0.006
Split Flow Ratio= 0.02
Log Output Level= 0
Friction Slope Method= 1
Unsteady Friction Slope Method= 2
Unsteady Bridges Friction Slope Method= 1
Parabolic Critical Depth
Global Vel Dist= 0 , 0 , 0
Global Log Level= 0
CheckData=True
Encroach Param=-1 ,0,0, 0
Flow Ratio Tolerance=0.1
Flow Ratio Min Ratio=0.5
Flow Ratio Max Ratio=4
Flow Ratio Max Iterations= 10
Computation Interval=1MIN
Output Interval=1HOUR
Instantaneous Interval=1HOUR
Mapping Interval=1HOUR
Computation Time Step Use Courant=        0
Computation Time Step Use Time Series=    0
Computation Time Step Count To Double=0
Computation Time Step Max Doubling=0
Computation Time Step Max Halving=0
Computation Time Step Residence Courant=0
Run HTab= 0
Run UNet= 0
Run Sediment= 0
Run PostProcess= 0
Run WQNet= 0
Run RASMapper= 0
UNET Theta= 1
UNET Theta Warmup= 1
UNET ZTol= 0.006
UNET ZSATol= 0.006
UNET MxIter= 20
UNET Max Iter WO Improvement= 0
UNET MaxInSteps= 0
UNET DtIC= 0
UNET DtMin= 0
UNET MaxCRTS= 20
UNET WFStab= 2
UNET SFStab= 1
UNET WFX= 1
UNET SFX= 1
UNET Gravity=9.80665
UNET 1D Methodology=Finite Difference
UNET DSS MLevel= 4
UNET Pardiso=0
UNET DZMax Abort= 30
UNET Use Existing IB Tables=-1
UNET Froude Reduction=False
UNET Froude Limit= 0.8
UNET Froude Power= 4
UNET D1 Cores= 0
UNET WindReference=Eulerian
UNET WindDragFormulation=Hsu (1988)
UNET D2 Coriolis=0
UNET D2 Cores= 0
UNET D2 Theta= 1
UNET D2 Theta Warmup= 1
UNET D2 Z Tol= 0.003
UNET D2 Volume Tol= 0.003
UNET D2 Max Iterations= 20
UNET D2 Equation= 0
UNET D2 RampUpFraction=0.1
UNET D2 TimeSlices= 1
UNET D2 Turbulence Formulation=None
UNET D2 Eddy Viscosity=0.3
UNET D2 Transverse Eddy Viscosity=0.1
UNET D2 Smagorinsky Mixing=0.05
UNET D2 BCVolumeCheck=0
UNET D2 Cores=0
UNET D2 SolverType=PARDISO (Direct)
UNET D2 Minimum Iterations= 3
UNET D2 Maximum Iterations= 30
UNET D2 Restart Number= 10
UNET D2 Relaxation Coeff=1.3
UNET D2 SOR Precondition Iterations= 10
UNET D2 ILUT Maximum Fill= 8
UNET D2 ILUT Tolerance=1E-08
UNET D2 Convergence Tolerance=0.00001
UNET D1D2 MaxIter= 0
UNET D1D2 ZTol=0.003
UNET D1D2 QTol=0.1
UNET D1D2 MinQTol=0.03
DSS File=dss
Write IC File= 0
Write IC File at Fixed DateTime=0
Write IC File at Sim End=0
Echo Input=False
Echo Parameters=False
Echo Output=False
Write Detailed= 0
HDF Write Warmup=0
HDF Write Time Slices=0
HDF Flush=0
HDF Compression= 1
HDF Chunk Size= 1
HDF Spatial Parts= 1
HDF Use Max Rows=0
HDF Fixed Rows= 1
Calibration Method= 0
Calibration Iterations= 20
Calibration Max Change=0.05
Calibration Tolerance=0.2
Calibration Maximum=1.5
Calibration Minimum=0.5
Calibration Optimization Method= 1
WQ AD Non Conservative
WQ ULTIMATE=-1
WQ Max Comp Step=1HOUR
WQ Output Interval=15MIN
WQ Output Selected Increments= 0
WQ Create Restart=0
WQ Fixed Restart=0
WQ System Summary=0
WQ Write To DSS=0
Sorting and Armoring Iterations= 10
XS Update Threshold= 0.02
Bed Roughness Predictor= 0
Hydraulics Update Threshold= 0.02
Energy Slope Method= 1
Volume Change Method= 1
Sediment Retention Method= 0
Sediment TS Multiplier= 1
Warm Up Method= 0
XS Weighting Method= 0
Number of US Weighted Cross Sections= 1
Number of DS Weighted Cross Sections= 1
Upstream XS Weight=0
Main XS Weight=1
Downstream XS Weight=0
Number of DS XS's Weighted with US Boundary= 1
Upstream Boundary Weight= 1
Weight of XSs Associated with US Boundary= 0
Number of US XS's Weighted with DS Boundary= 1
Downstream Boundary Weight= 0.5
Weight of XSs Associated with DS Boundary= 0.5
Percentile Method= 0
Sediment Output Level= 3
Mass or Volume Output= 0
Output Increment Type= 1
Profile and TS Output Increment= 1
Transport Output Increment 1
XS Output Flag= 0
XS Output Increment= 10
Read HDF5 Sediment Hotstart= 0
Sediment Hotstart Type= 0
Write Gradation File= 0
Read Gradation Hotstart= 0
Write HDF5 File= 1
Write Binary Output= 1
Write DSS Sediment File= 0
DSS Sediment Output Type= 1
SV Curve= 0
Specific Gage Flag= 0
Subcell Erosion Methods= 0
Subcell Deposition Methods= 0
Advection Scheme= 1
Matrix Solver= 0
Implicit Weighting Factor= 1
Maximum Outer Loop Convergence Iterations= 5
Convergence Maximum Absolute= 0.001
Convergence RMSE= 0.0001
Grain Fractions Max Abs Error= 0.001
Max Subgrid Regions= 1
Max Subgrid Length Scale= 3.402823E+38
Initial Layer Thickness= 3
Min Layer Thickness= 0.1
Max Layer Thickness= 6
Number of Layers= 5

--- RiverDhiprangMode.f01 (steady flow) ---

Flow Title=Dhiprang_Steady_Data
Program Version=6.41
Number of Profiles= 3
Profile Names=Q50,Q100,Q1000
River Rch & RM=Dhiprang,Tuse            ,15
  72.726  87.212  152.24
Boundary for River Rch & Prof#=Dhiprang,Tuse            , 1
Up Type= 0
Dn Type= 3
Dn Slope=0.0555
Boundary for River Rch & Prof#=Dhiprang,Tuse            , 2
Up Type= 0
Dn Type= 3
Dn Slope=0.0555
DSS Import GetInterval= 0
DSS Import GetPeak= 0
DSS Import FillOption= 0

--- RiverDhiprangMode.u01 (unsteady flow) ---

Flow Title=Dhiprang_Unsteady_Data
Program Version=6.41
Use Restart= 0
Boundary Location=Dhiprang        ,Tuse            ,15      ,        ,                ,                ,                ,                                ,
Boundary Location=Dhiprang        ,Tuse            ,1       ,        ,                ,                ,                ,                                ,
Precipitation Mode=Disable
Wind Mode=No Wind Forces
Met BC=Precipitation|Expanded View=0
Met BC=Precipitation|Point Interpolation=Nearest
Met BC=Precipitation|Gridded Source=DSS
Met BC=Evapotranspiration|Expanded View=0
Met BC=Evapotranspiration|Point Interpolation=Nearest
Met BC=Evapotranspiration|Gridded Source=DSS
Met BC=Wind Speed|Expanded View=0
Met BC=Wind Speed|Point Interpolation=Nearest
Met BC=Wind Speed|Gridded Source=DSS
Met BC=Wind Direction|Expanded View=0
Met BC=Wind Direction|Point Interpolation=Nearest
Met BC=Wind Direction|Gridded Source=DSS
Met BC=Wind Velocity X|Expanded View=0
Met BC=Wind Velocity X|Point Interpolation=Nearest
Met BC=Wind Velocity X|Gridded Source=DSS
Met BC=Wind Velocity Y|Expanded View=0
Met BC=Wind Velocity Y|Point Interpolation=Nearest
Met BC=Wind Velocity Y|Gridded Source=DSS
Met BC=Air Density|Mode=Constant
Met BC=Air Density|Expanded View=0
Met BC=Air Density|Constant Value=1.225
Met BC=Air Density|Constant Units=kg/m3
Met BC=Air Density|Point Interpolation=Nearest
Met BC=Air Density|Gridded Source=DSS
Met BC=Air Temperature|Expanded View=0
Met BC=Air Temperature|Point Interpolation=Nearest
Met BC=Air Temperature|Gridded Source=DSS
Met BC=Humidity|Expanded View=0
Met BC=Humidity|Point Interpolation=Nearest
Met BC=Humidity|Gridded Source=DSS
Met BC=Air Pressure|Mode=Constant
Met BC=Air Pressure|Expanded View=0
Met BC=Air Pressure|Constant Value=1013.2
Met BC=Air Pressure|Constant Units=mb
Met BC=Air Pressure|Point Interpolation=Inv Distance
Met BC=Air Pressure|Gridded Source=DSS
Non-Newtonian Method= 0 ,
Non-Newtonian Constant Vol Conc=0
Non-Newtonian Yield Method= 0 ,
Non-Newtonian Yield Coef=0, 0
User Yeild=   0
Non-Newtonian Sed Visc= 0 ,
Non-Newtonian Obrian B=0
User Viscosity=0
User Viscosity Ratio=0
Herschel-Bulkley Coef=0, 0
Clastic Method= 0 ,
Coulomb Phi=0
Voellmy X=0
Non-Newtonian Hindered FV= 0
Non-Newtonian FV K=0
Non-Newtonian ds=0
Non-Newtonian Max Cv=0
Non-Newtonian Bulking Method= 0 ,
Non-Newtonian High C Transport= 0 ,
Lava Activation= 0
Temperature=1300,15,,15,14,980
Heat Ballance=1,1200,0.5,1,70,0.95
Viscosity=1000,,,
Profile Coefficient=4,1.3,
Lava Param=,2500,

--- RiverDhiprangMode.g03 (geometry) ---

Geom Title=Dhiprang Geometry with bridge
Program Version=6.41

River Reach=Dhiprang        ,Tuse
Reach XY= 16
789350.6133362313139552.92505458789376.4054087383139548.44398618
789398.3563001173139546.48500068789423.3620864183139548.81424262
 789448.038094873139547.19393827789474.6359138723139543.05938014
789501.5959688593139537.08426825789525.5016999223139534.40399919
789549.1512588753139542.29678878789570.6442261153139542.86629651
789592.5396789033139535.00093969 789608.036549763139524.87376474
789633.9329000333139520.82300005789655.2306496533139507.84333719
789678.8789003763139496.18900067789708.2942288683139489.53657123

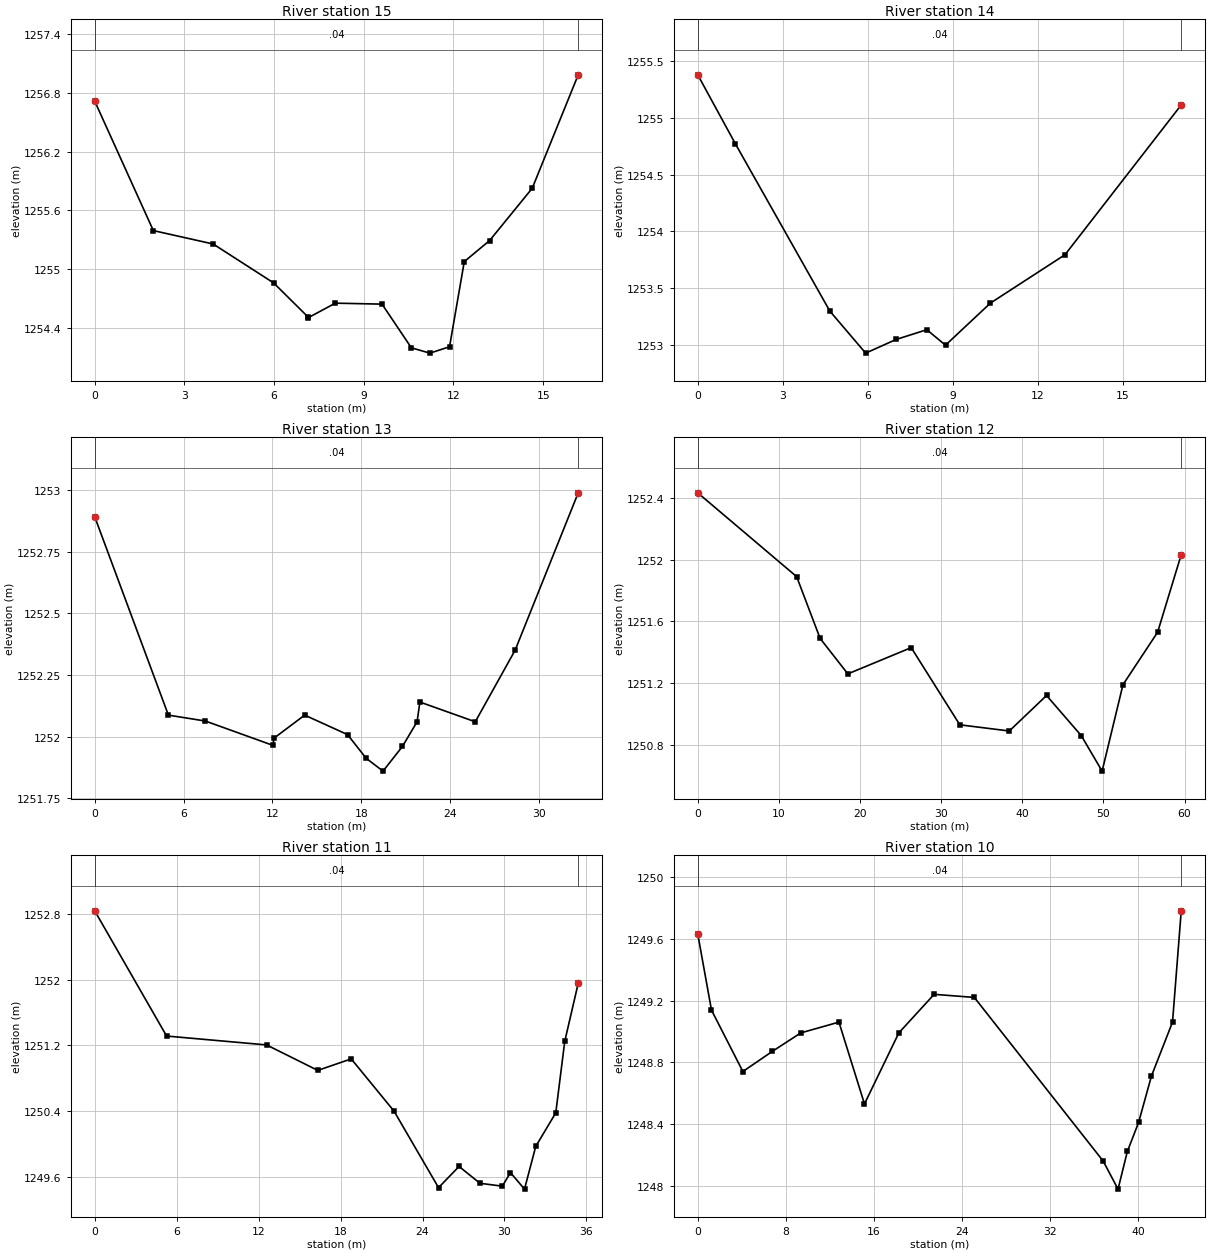
Type RM Length L Ch R = 1 ,15      ,12.5,12.5,12.5
XS GIS Cut Line= 6
     789356.1186     3139543.543     789354.7602     3139544.957
     789354.1334     3139546.858     789351.5448     3139549.904
     789350.4423     3139553.541     789350.0317     3139557.791
#Sta/Elev= 15
       01256.718   1.9611255.394   3.9621255.257   5.9851254.859   7.1311254.512
   7.1361254.502   8.0481254.652   9.6111254.642  10.5931254.195  11.2131254.141
  11.8691254.206  12.3621255.077  13.2091255.292  14.6351255.827  16.1731256.987
#Mann= 3 ,0,0
       0    .045       0       0     .04       0  16.173    .045       0
Bank Sta=0,16.173
XS Rating Curve= 0 ,0
Exp/Cntr=0.3,0.1

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
Type RM Length L Ch R = 1 ,14      ,12.5,12.5,12.5
XS GIS Cut Line= 6
     789375.2332     3139541.742     789375.7637     3139542.956
     789375.8166     3139547.546     789377.0035      3139550.06
     789377.4946     3139554.239     789379.4622     3139557.834
#Sta/Elev= 10
       01255.378   1.3251254.772   4.6611253.298   5.9221252.929   6.9931253.049
   8.0781253.135   8.7381252.999  10.3211253.369  12.9531253.795  17.0521255.113
#Mann= 3 ,0,0
       0    .045       0       0     .04       0  17.052    .045       0
Bank Sta=0,17.052
XS Rating Curve= 0 ,0
Exp/Cntr=0.3,0.1

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
Type RM Length L Ch R = 1 ,13      ,12.5,12.5,12.5
XS GIS Cut Line= 6
     789400.2282     3139536.995     789398.3071     3139543.763
     789399.5127      3139542.02     789398.3563     3139546.485
      789399.125     3139550.929     789398.5878     3139547.572
#Sta/Elev= 15
       01252.891   4.9751252.087   7.4751252.063  12.0551251.964  12.0941251.993
   14.181252.087  17.0731252.008  18.3331251.912   19.47 1251.86   20.78 1251.96
   21.77 1252.06   21.96 1252.14    25.7 1252.06   28.39 1252.35  32.6521252.988
#Mann= 3 ,0,0
       0    .045       0       0     .04       0  32.652    .045       0
Bank Sta=0,32.652
XS Rating Curve= 0 ,0
Exp/Cntr=0.3,0.1

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
Type RM Length L Ch R = 1 ,12      ,12.5,12.5,12.5
XS GIS Cut Line= 6
     789426.4613      3139536.56789421.6675912983139550.04660271
789422.1913443353139551.49462581789421.1130292593139551.92595184
 789424.101502473139553.71287396789425.9192335983139556.82458318
#Sta/Elev= 13
       01252.433   12.19 1251.89   15.08 1251.49    18.5 1251.26   26.31 1251.43
    32.3 1250.93    38.4 1250.89   42.99 1251.12   47.27 1250.86   49.84 1250.63
   52.41 1251.19   56.68 1251.53  59.5921252.033
#Mann= 3 ,0,0
       0    .045       0       0     .04       0  59.592    .045       0
Bank Sta=0,59.592
XS Rating Curve= 0 ,0
Exp/Cntr=0.3,0.1

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
Type RM Length L Ch R = 1 ,11      ,12.5,12.5,12.5
XS GIS Cut Line= 6
     789440.8239     3139527.807     789448.2865     3139537.921
     789447.8692     3139541.646     789448.4574      3139550.42
     789446.7115     3139555.429     789447.6621     3139556.694
#Sta/Elev= 16
       01252.836   5.2631251.312  12.5821251.204  16.3311250.894   18.781251.034
  21.9141250.398  25.1711249.467  26.6741249.725  28.205 1249.52  29.8441249.485
  30.434 1249.65  31.4651249.449  32.2881249.969  33.7541250.377  34.4121251.248
  35.3971251.954
#Mann= 3 ,0,0
       0    .045       0       0     .04       0  35.397    .045       0
Bank Sta=0,35.397
XS Rating Curve= 0 ,0
Exp/Cntr=0.3,0.1

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
Type RM Length L Ch R = 1 ,10      ,12.5,12.5,12.5
XS GIS Cut Line= 6
789468.7359366033139523.03069415789474.4290998323139534.85561814
789473.7262401743139540.12946415789478.0111792973139549.16396115
789477.9047022333139554.59429144789479.6793199773139554.98470735
#Sta/Elev= 17
       01249.631   1.2481249.138     4.1 1248.74    6.77 1248.87    9.36 1248.99
   12.83 1249.06   15.15 1248.53   18.27 1248.99   21.48 1249.24   25.13 1249.22
  36.837 1248.16   38.191247.978  39.0361248.222  40.058 1248.41  41.2271248.711
   43.14 1249.06  43.9331249.781
#Mann= 3 ,0,0
       0    .045       0       0     .04       0  43.933    .045       0
Bank Sta=0,43.933
XS Rating Curve= 0 ,0
Exp/Cntr=0.3,0.1

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
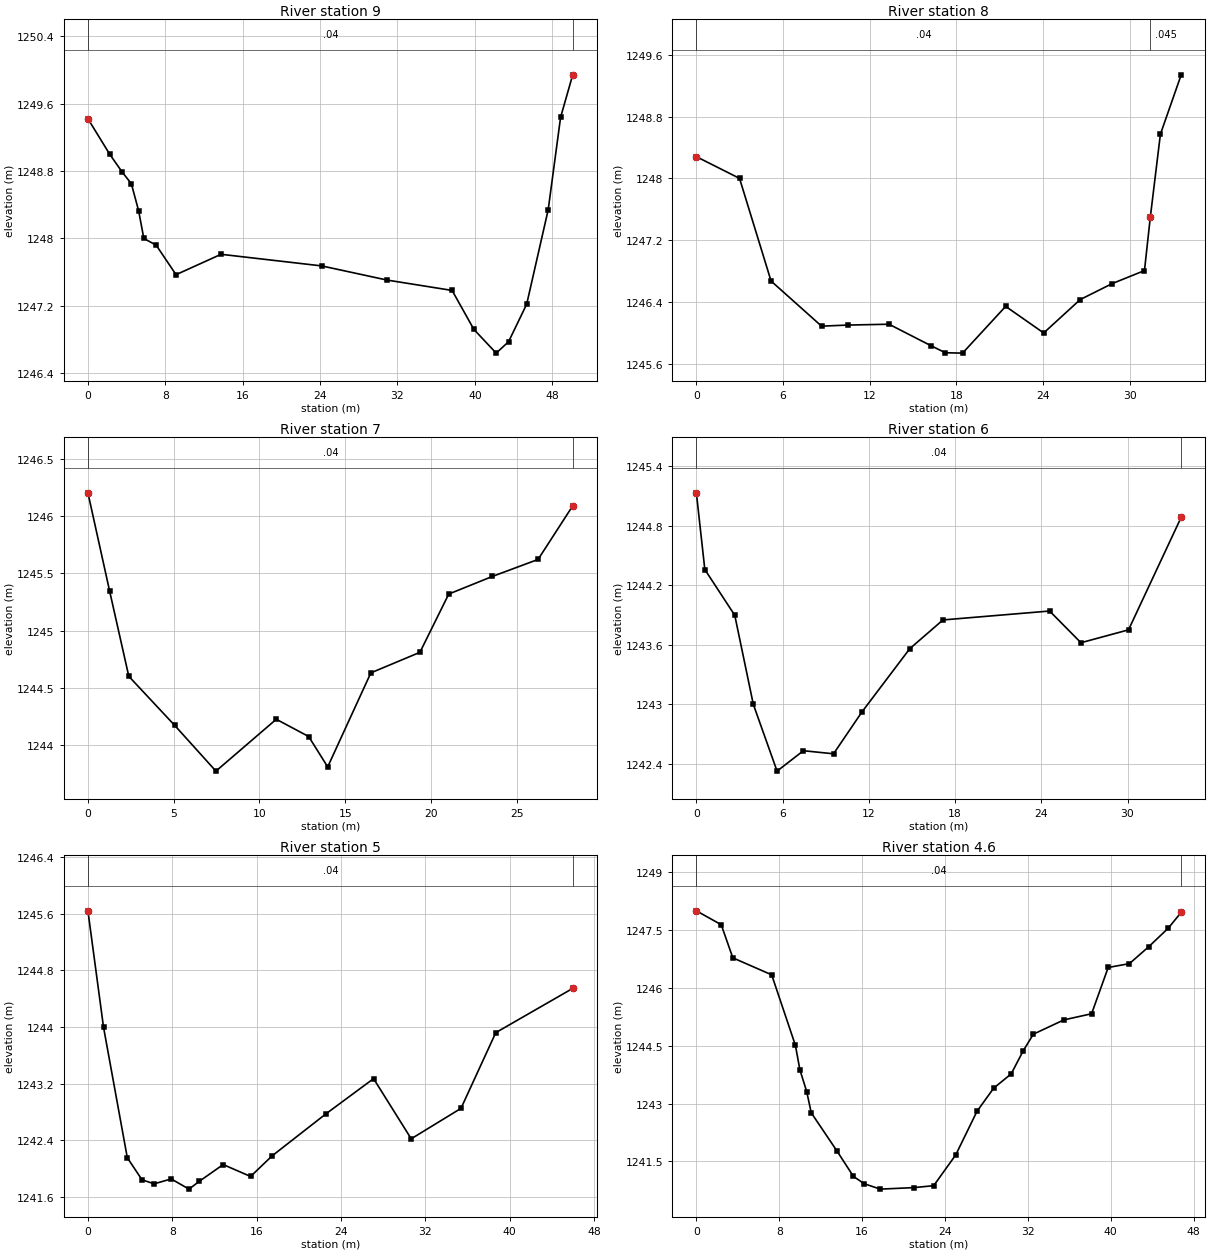
Type RM Length L Ch R = 1 ,9       ,12.5,12.5,12.5
XS GIS Cut Line= 6
789497.4507123073139520.79110708789495.1477920013139525.05150965
789500.4445087063139531.03910244789499.6384865983139533.22687673
     789501.7414      3139541.11     789506.3879       3139550.1
#Sta/Elev= 19
       01249.421    2.25    1249    3.53 1248.79    4.49 1248.65    5.24 1248.33
    5.78    1248    7.06 1247.92   9.111 1247.57  13.7641247.812   24.171247.674
  30.9281247.506  37.6471247.383  39.8961246.921  42.2041246.639  43.4821246.774
  45.357 1247.22   47.581248.341  48.8621249.438  50.1151249.942
#Mann= 3 ,0,0
       0    .045       0       0     .04       0  50.115    .045       0
Bank Sta=0,50.115
XS Rating Curve= 0 ,0
Exp/Cntr=0.3,0.1

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
Type RM Length L Ch R = 1 ,8       ,12.5,12.5,12.5
XS GIS Cut Line= 6
     789522.3732     3139517.204      789521.013      3139522.19
     789525.4163     3139532.235     789526.5112     3139537.214
     789526.4459     3139544.564789529.1054913693139548.45060359
#Sta/Elev= 17
       01248.281    2.99    1248   5.1721246.672   8.6691246.088  10.4771246.102
   13.341246.113  16.2571245.834  17.2391245.744  18.4321245.739  21.4171246.344
   24.05    1246  26.5791246.432  28.7961246.639  31.0281246.807  31.4331247.498
   32.13 1248.57   33.57 1249.34
#Mann= 3 ,0,0
       0    .045       0       0     .04       0  31.433    .045       0
Bank Sta=0,31.433
XS Rating Curve= 0 ,0
Exp/Cntr=0.3,0.1

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
Type RM Length L Ch R = 1 ,7       ,12.5,12.5,12.5
XS GIS Cut Line= 6
     789551.0472     3139535.243     789549.9835     3139537.375
789548.8777714053139541.76229291789549.4004735463139542.88584164
     789547.4189     3139551.175     789545.9407     3139555.621
#Sta/Elev= 14
       01246.206    1.26 1245.35   2.383  1244.6    5.06 1244.17   7.461 1243.77
  10.9781244.224  12.8661244.073  13.9751243.807   16.49 1244.63   19.35 1244.81
   21.03 1245.32  23.5691245.474  26.2361245.623  28.2551246.092
#Mann= 3 ,0,0
       0    .045       0       0     .04       0  28.255    .045       0
Bank Sta=0,28.255
XS Rating Curve= 0 ,0
Exp/Cntr=0.3,0.1

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
Type RM Length L Ch R = 1 ,6       ,12.5,12.5,12.5
XS GIS Cut Line= 6
789566.9970298243139529.68740967789566.7190365823139531.96695425
789568.3058767893139537.62272529789570.0773535513139541.16567882
789572.8408573013139550.73165334789574.8249112753139554.13288872
#Sta/Elev= 14
       01245.133    .5891244.359   2.6721243.897   3.9631242.998   5.6161242.324
   7.448 1242.53   9.5451242.499   11.531242.923   14.85 1243.56   17.16 1243.85
   24.58 1243.94   26.76 1243.62   30.07 1243.75  33.7341244.886
#Mann= 3 ,0,0
       0    .045       0       0     .04       0  33.734    .045       0
Bank Sta=0,33.734
XS Rating Curve= 0 ,0
Exp/Cntr=0.3,0.1

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
Type RM Length L Ch R = 1 ,5       ,12.5,12.5,12.5
XS GIS Cut Line= 6
     789587.0866     3139524.846     789589.5473     3139532.292
     789591.2319     3139532.194 789599.342145723139545.69502577
789598.9022763773139549.70883352789597.6376520163139549.65384985
#Sta/Elev= 17
       01245.641   1.4791243.999   3.7361242.153   5.1281241.841   6.2811241.784
   7.9011241.853   9.5881241.709  10.571 1241.82  12.8281242.056  15.4271241.888
  17.4691242.179   22.55 1242.77   27.09 1243.27   30.66 1242.42   35.38 1242.85
   38.68 1243.92  45.9761244.545
#Mann= 3 ,0,0
       0    .045       0       0     .04       0  45.976    .045       0
Bank Sta=0,45.976
XS Rating Curve= 0 ,0
Exp/Cntr=0.3,0.1

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
Type RM Length L Ch R = 1 ,4.6     ,50,50,50
XS GIS Cut Line= 6
789601.6486928573139516.89984828789602.1297066833139517.83655942
789602.5929692283139518.61910332789606.4841476413139525.86189537
 789610.281625223139533.02646973789611.5980841143139535.35558932
#Sta/Elev= 27
       0    1248     2.4 1247.64    3.52 1246.78    7.27 1246.34    9.56 1244.51
    9.99 1243.88   10.65 1243.31   11.09 1242.76   13.57 1241.77   15.16 1241.11
    16.2 1240.92   17.75 1240.78   21.05 1240.82   22.91 1240.87   25.04 1241.67
   27.09  1242.8    28.7  1243.4   30.39 1243.77   31.55 1244.37   32.53  1244.8
   35.47 1245.17   38.15 1245.33   39.75 1246.53    41.8 1246.63   43.67 1247.07
   45.55 1247.55  46.796 1247.96
#Mann= 3 ,0,0
       0    .045       0       0     .04       0  46.796    .045       0
Bank Sta=0,46.796
XS Rating Curve= 0 ,0
Exp/Cntr=0.3,0.1

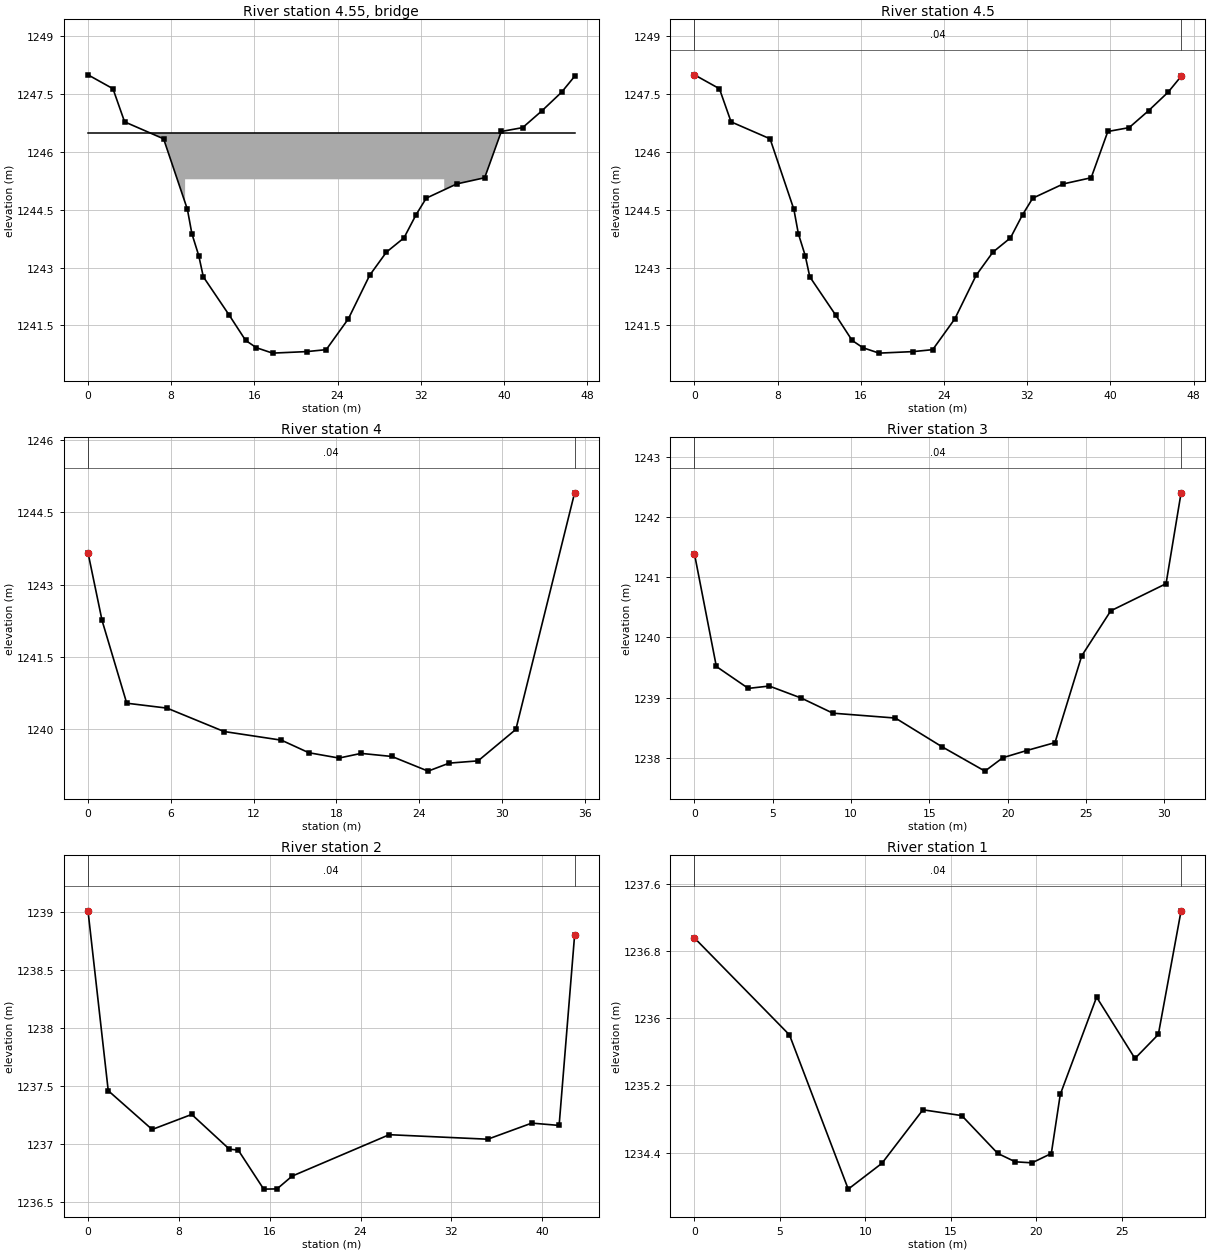
Type RM Length L Ch R = 3 ,4.55    ,,,
Bridge Culvert--1,0,-1,-1, 0
Deck Dist Width WeirC Skew NumUp NumDn MinLoCord MaxHiCord MaxSubmerge Is_Ogee
20,8.6,1.4,0, 6, 6, , , 0.98, 0, 0,0,,
       0    9.34    9.34   34.26   34.26    46.8
  1246.5  1246.5  1246.5  1246.5  1246.5  1246.5
 1244.82    1244 1245.29 1245.29    1244 1244.82
       0    9.34    9.34   34.26   34.26    46.8
  1246.5  1246.5  1246.5  1246.5  1246.5  1246.5
 1244.82    1244 1245.29 1245.29    1244 1244.82
BR Coef=-1 , 0 , 0 ,, 0 ,,,0.8,-1,,0,
WSPro=,,,, 1 ,,,, 0 ,,,, 0 ,,,,-1 ,-1 ,-1 , 0 , 0 , 0 , 0 , 0
BC Design=,, 0 ,, 0 ,,,,,,
BC Use User HTab Curves=0
BC User HTab FreeFlow(D)= 0

Type RM Length L Ch R = 1 ,4.5     ,16.667,16.667,16.667
XS GIS Cut Line= 6
789603.2010949763139515.88640114789603.6821088033139516.82311228
789604.1453713483139517.60565618789605.0492007323139519.32944748
789606.1884440053139521.45603492789613.155438229 3139534.3408393
#Sta/Elev= 27
       0    1248     2.4 1247.64    3.52 1246.78    7.27 1246.34    9.56 1244.51
    9.99 1243.88   10.65 1243.31   11.09 1242.76   13.57 1241.77   15.16 1241.11
    16.2 1240.92   17.75 1240.78   21.05 1240.82   22.91 1240.87   25.04 1241.67
   27.09  1242.8    28.7  1243.4   30.39 1243.77   31.55 1244.37   32.53  1244.8
   35.47 1245.17   38.15 1245.33   39.75 1246.53    41.8 1246.63   43.67 1247.07
   45.55 1247.55  46.796 1247.96
#Mann= 3 ,0,0
       0    .045       0       0     .04       0  46.796    .045       0
Bank Sta=0,46.796
XS Rating Curve= 0 ,0
Exp/Cntr=0.3,0.1

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
Type RM Length L Ch R = 1 ,4       ,12.5,12.5,12.5
XS GIS Cut Line= 6
     789622.9774     3139499.105     789626.5074     3139503.533
      789629.539     3139511.244     789631.5301     3139514.912
     789632.5216     3139518.613     789639.6194     3139529.779
#Sta/Elev= 15
       01243.666   1.019 1242.26   2.8071240.544   5.7281240.442   9.8541239.957
  14.0191239.777      161239.517  18.1931239.406  19.7911239.503  22.0251239.439
  24.6471239.135  26.1781239.301  28.2711239.348  31.0091240.001  35.2671244.908
#Mann= 3 ,0,0
       0    .045       0       0     .04       0  35.267    .045       0
Bank Sta=0,35.267
XS Rating Curve= 0 ,0
Exp/Cntr=0.3,0.1

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
Type RM Length L Ch R = 1 ,3       ,12.5,12.5,12.5
XS GIS Cut Line= 6
     789649.5466     3139493.536     789654.1368      3139500.91
     789655.2929     3139507.744     789661.3001     3139516.514
     789662.7122      3139519.75     789662.1709     3139520.543
#Sta/Elev= 16
       01241.387   1.3981239.516   3.4391239.152   4.7791239.191    6.83 1238.99
   8.839 1238.74  12.8331238.659  15.7831238.186  18.5511237.777  19.692    1238
  21.2141238.119  23.0241238.251  24.7321239.693  26.5861240.441  30.1171240.892
  31.0771242.402
#Mann= 3 ,0,0
       0    .045       0       0     .04       0  31.077    .045       0
Bank Sta=0,31.077
XS Rating Curve= 0 ,0
Exp/Cntr=0.3,0.1

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
Type RM Length L Ch R = 1 ,2       ,15,15,15
XS GIS Cut Line= 6
     789675.8572      3139486.36789678.4840898013139490.27002827
     789678.8789     3139496.189789682.7789002753139498.93566356
     789678.9313     3139500.317     789679.3117     3139506.199
#Sta/Elev= 14
       01239.012   1.7821237.459   5.6491237.124   9.1331237.254  12.4491236.954
  13.2291236.946  15.4721236.609  16.6481236.611  17.9671236.721  26.5281237.079
    35.2 1237.04  39.0751237.179  41.4851237.159   42.851238.803
#Mann= 3 ,0,0
       0    .045       0       0     .04       0   42.85    .045       0
Bank Sta=0,42.85
XS Rating Curve= 0 ,0
Exp/Cntr=0.3,0.1

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
Type RM Length L Ch R = 1 ,1       ,0,0,0
XS GIS Cut Line= 6
789703.3782017773139482.09599964     789707.3919      3139480.74
     789708.2682     3139489.416     789709.6778     3139494.462
     789710.0779     3139494.802     789711.0226     3139501.786
#Sta/Elev= 15
       01236.954    5.56  1235.8   8.9981233.965  10.9721234.273  13.3681234.909
  15.642 1234.84  17.746 1234.39  18.773 1234.29  19.7521234.278  20.8811234.389
  21.4061235.093   23.53 1236.25  25.775 1235.52  27.1431235.806  28.4741237.277
#Mann= 3 ,0,0
       0    .045       0       0     .04       0  28.474    .045       0
Bank Sta=0,28.474
XS Rating Curve= 0 ,0
Exp/Cntr=0.3,0.1
LCMann Table=0

Chan Stop Cuts=-1
Use User Specified Reach Order=0
Composite Channel Slope=5

--- RiverDhiprangMode.g02 (geometry) ---

Geom Title=Dhiprang Geometry
Program Version=6.41

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
River Reach=Dhiprang        ,Tuse

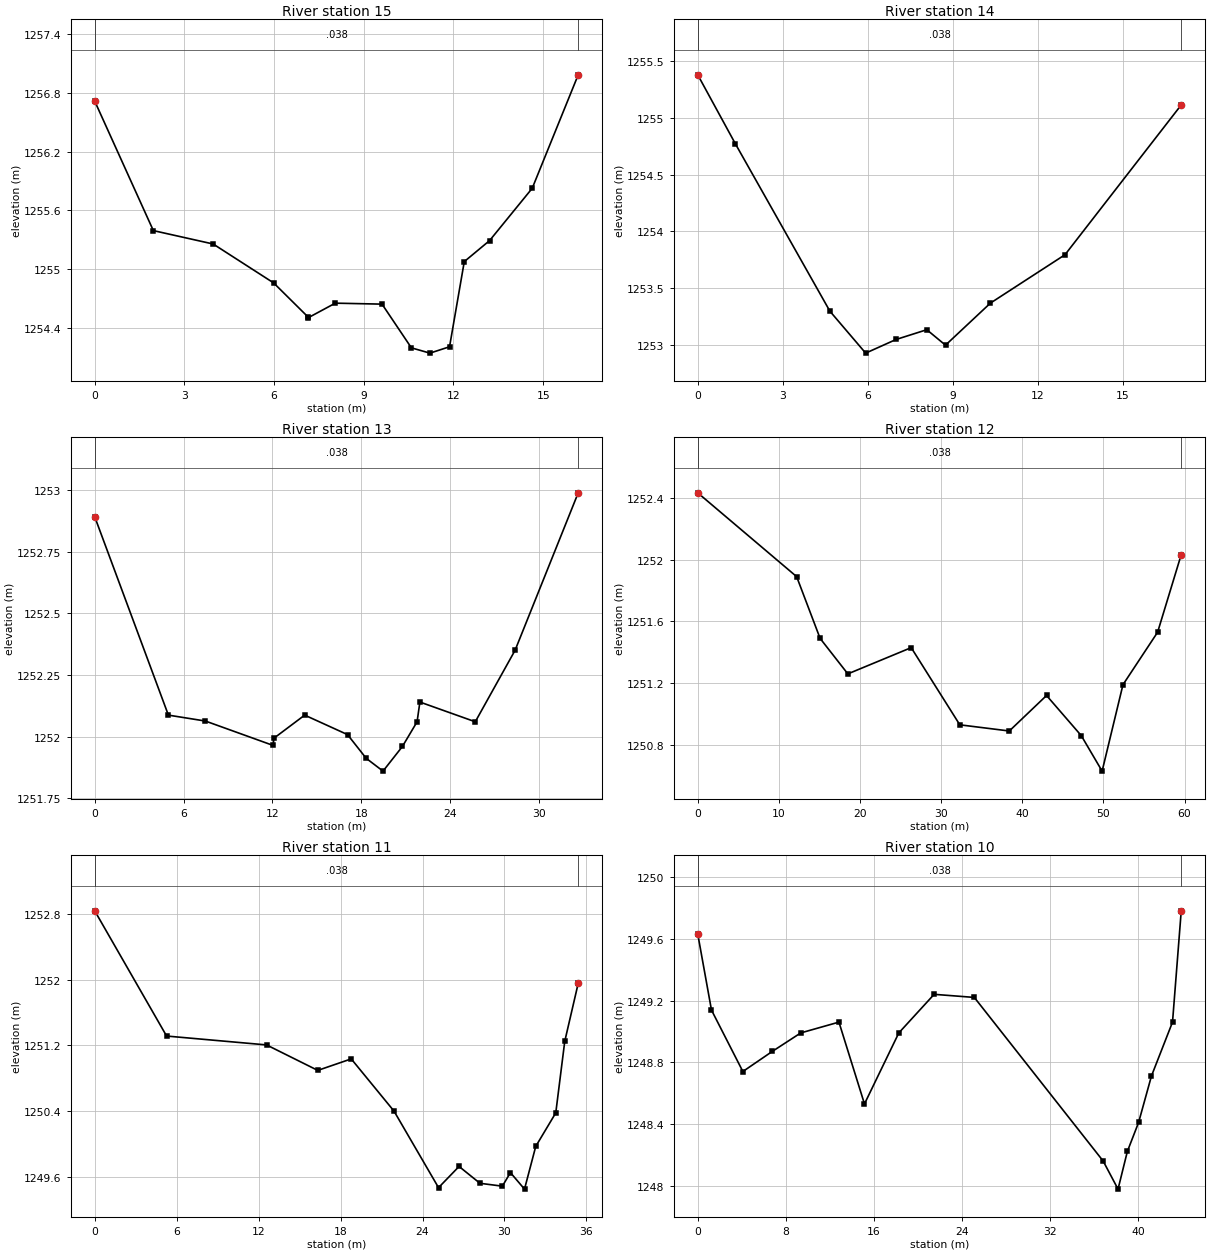
Type RM Length L Ch R = 1 ,15      ,25,25,25
XS GIS Cut Line= 6
     789356.1186     3139543.543     789354.7602     3139544.957
     789354.1334     3139546.858     789351.5448     3139549.904
     789350.4423     3139553.541     789350.0317     3139557.791
#Sta/Elev= 15
       01256.718   1.9611255.394   3.9621255.257   5.9851254.859   7.1311254.512
   7.1361254.502   8.0481254.652   9.6111254.642  10.5931254.195  11.2131254.141
  11.8691254.206  12.3621255.077  13.2091255.292  14.6351255.827  16.1731256.987
#Mann= 3 ,0,0
       0     .05       0       0    .038       0  16.173     .05       0
Bank Sta=0,16.173
XS Rating Curve= 0 ,0
Exp/Cntr=0.3,0.1

Type RM Length L Ch R = 1 ,14      ,25,25,25
XS GIS Cut Line= 6
     789375.2332     3139541.742     789375.7637     3139542.956
     789375.8166     3139547.546     789377.0035      3139550.06
     789377.4946     3139554.239     789379.4622     3139557.834
#Sta/Elev= 10
       01255.378   1.3251254.772   4.6611253.298   5.9221252.929   6.9931253.049
   8.0781253.135   8.7381252.999  10.3211253.369  12.9531253.795  17.0521255.113
#Mann= 3 ,0,0
       0     .05       0       0    .038       0  17.052     .05       0
Bank Sta=0,17.052
XS Rating Curve= 0 ,0
Exp/Cntr=0.3,0.1

Type RM Length L Ch R = 1 ,13      ,25,25,25
XS GIS Cut Line= 6
     789400.2282     3139536.995     789398.3071     3139543.763
     789399.5127      3139542.02     789398.3563     3139546.485
      789399.125     3139550.929     789398.5878     3139547.572
#Sta/Elev= 15
       01252.891   4.9751252.087   7.4751252.063  12.0551251.964  12.0941251.993
   14.181252.087  17.0731252.008  18.3331251.912   19.47 1251.86   20.78 1251.96
   21.77 1252.06   21.96 1252.14    25.7 1252.06   28.39 1252.35  32.6521252.988
#Mann= 3 ,0,0
       0     .05       0       0    .038       0  32.652     .05       0
Bank Sta=0,32.652
XS Rating Curve= 0 ,0
Exp/Cntr=0.3,0.1

Type RM Length L Ch R = 1 ,12      ,25,25,25
XS GIS Cut Line= 6
     789426.4613      3139536.56789421.6675912983139550.04660271
789422.1913443353139551.49462581789421.1130292593139551.92595184
 789424.101502473139553.71287396789425.9192335983139556.82458318
#Sta/Elev= 13
       01252.433   12.19 1251.89   15.08 1251.49    18.5 1251.26   26.31 1251.43
    32.3 1250.93    38.4 1250.89   42.99 1251.12   47.27 1250.86   49.84 1250.63
   52.41 1251.19   56.68 1251.53  59.5921252.033
#Mann= 3 ,0,0
       0     .05       0       0    .038       0  59.592     .05       0
Bank Sta=0,59.592
XS Rating Curve= 0 ,0
Exp/Cntr=0.3,0.1

Type RM Length L Ch R = 1 ,11      ,25,25,25
XS GIS Cut Line= 6
     789440.8239     3139527.807     789448.2865     3139537.921
     789447.8692     3139541.646     789448.4574      3139550.42
     789446.7115     3139555.429     789447.6621     3139556.694
#Sta/Elev= 16
       01252.836   5.2631251.312  12.5821251.204  16.3311250.894   18.781251.034
  21.9141250.398  25.1711249.467  26.6741249.725  28.205 1249.52  29.8441249.485
  30.434 1249.65  31.4651249.449  32.2881249.969  33.7541250.377  34.4121251.248
  35.3971251.954
#Mann= 3 ,0,0
       0     .05       0       0    .038       0  35.397     .05       0
Bank Sta=0,35.397
XS Rating Curve= 0 ,0
Exp/Cntr=0.3,0.1

Type RM Length L Ch R = 1 ,10      ,25,25,25
XS GIS Cut Line= 6
789468.7359366033139523.03069415789474.4290998323139534.85561814
789473.7262401743139540.12946415789478.0111792973139549.16396115
789477.9047022333139554.59429144789479.6793199773139554.98470735
#Sta/Elev= 17
       01249.631   1.2481249.138     4.1 1248.74    6.77 1248.87    9.36 1248.99
   12.83 1249.06   15.15 1248.53   18.27 1248.99   21.48 1249.24   25.13 1249.22
  36.837 1248.16   38.191247.978  39.0361248.222  40.058 1248.41  41.2271248.711
   43.14 1249.06  43.9331249.781
#Mann= 3 ,0,0
       0     .05       0       0    .038       0  43.933     .05       0
Bank Sta=0,43.933
XS Rating Curve= 0 ,0
Exp/Cntr=0.3,0.1

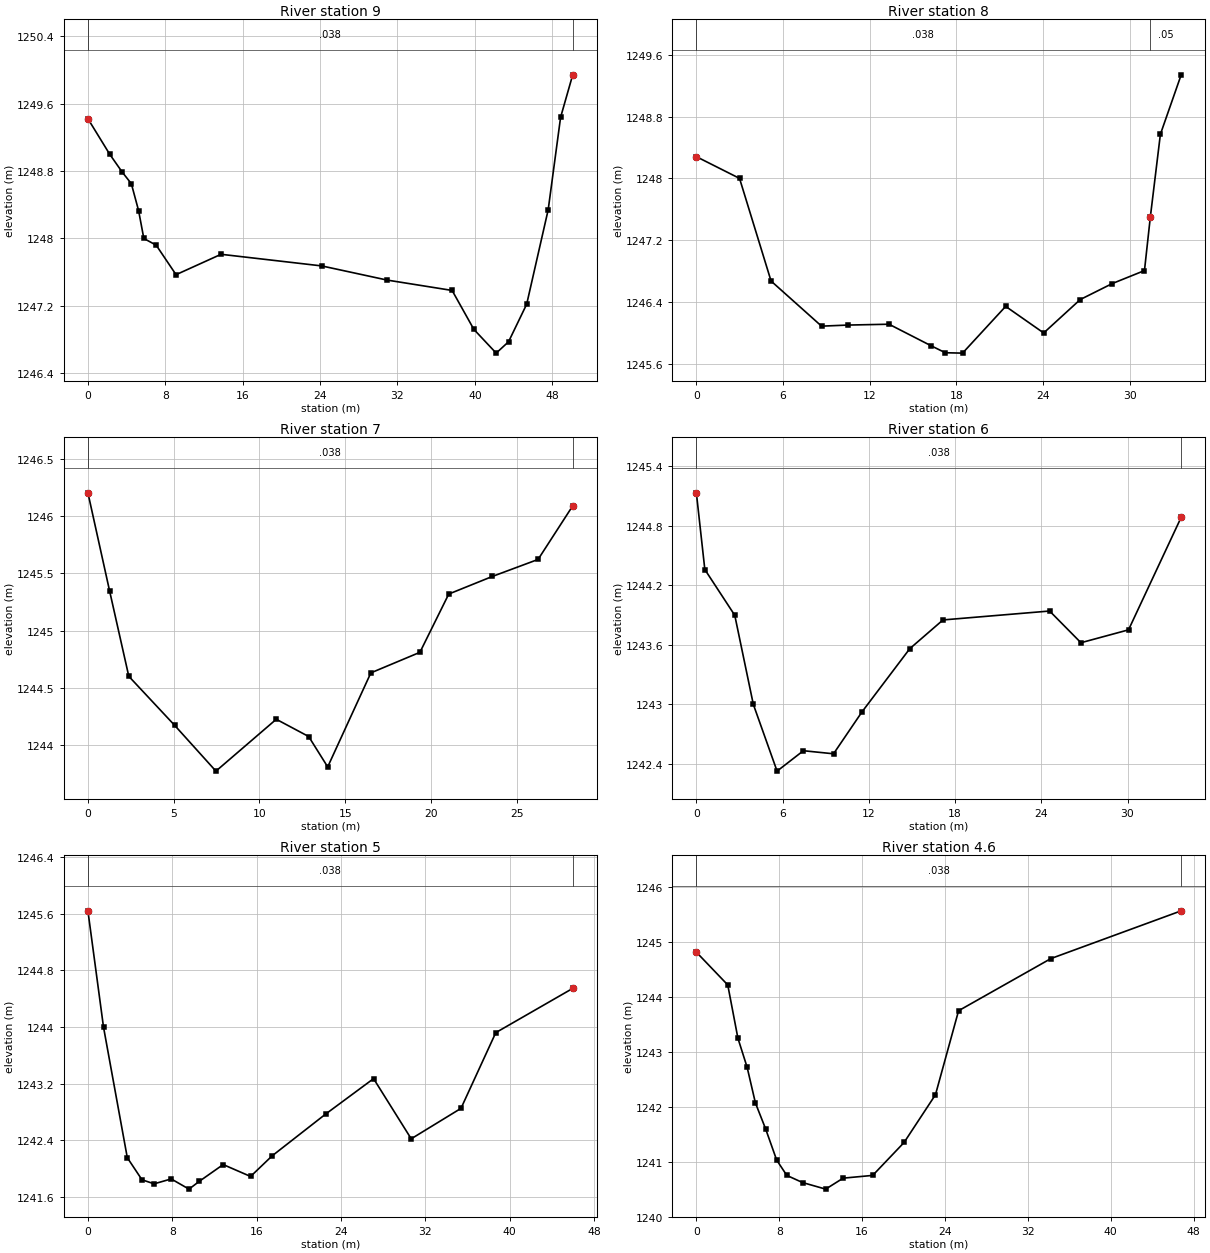
Type RM Length L Ch R = 1 ,9       ,25,25,25
XS GIS Cut Line= 6
789497.4507123073139520.79110708789495.1477920013139525.05150965
789500.4445087063139531.03910244789499.6384865983139533.22687673
     789501.7414      3139541.11     789506.3879       3139550.1
#Sta/Elev= 19
       01249.421    2.25    1249    3.53 1248.79    4.49 1248.65    5.24 1248.33
    5.78    1248    7.06 1247.92   9.111 1247.57  13.7641247.812   24.171247.674
  30.9281247.506  37.6471247.383  39.8961246.921  42.2041246.639  43.4821246.774
  45.357 1247.22   47.581248.341  48.8621249.438  50.1151249.942
#Mann= 3 ,0,0
       0     .05       0       0    .038       0  50.115     .05       0
Bank Sta=0,50.115
XS Rating Curve= 0 ,0
Exp/Cntr=0.3,0.1

Type RM Length L Ch R = 1 ,8       ,25,25,25
XS GIS Cut Line= 6
     789522.3732     3139517.204      789521.013      3139522.19
     789525.4163     3139532.235     789526.5112     3139537.214
     789526.4459     3139544.564789529.1054913693139548.45060359
#Sta/Elev= 17
       01248.281    2.99    1248   5.1721246.672   8.6691246.088  10.4771246.102
   13.341246.113  16.2571245.834  17.2391245.744  18.4321245.739  21.4171246.344
   24.05    1246  26.5791246.432  28.7961246.639  31.0281246.807  31.4331247.498
   32.13 1248.57   33.57 1249.34
#Mann= 3 ,0,0
       0     .05       0       0    .038       0  31.433     .05       0
Bank Sta=0,31.433
XS Rating Curve= 0 ,0
Exp/Cntr=0.3,0.1

Type RM Length L Ch R = 1 ,7       ,25,25,25
XS GIS Cut Line= 6
     789551.0472     3139535.243     789549.9835     3139537.375
789548.8777714053139541.76229291789549.4004735463139542.88584164
     789547.4189     3139551.175     789545.9407     3139555.621
#Sta/Elev= 14
       01246.206    1.26 1245.35   2.383  1244.6    5.06 1244.17   7.461 1243.77
  10.9781244.224  12.8661244.073  13.9751243.807   16.49 1244.63   19.35 1244.81
   21.03 1245.32  23.5691245.474  26.2361245.623  28.2551246.092
#Mann= 3 ,0,0
       0     .05       0       0    .038       0  28.255     .05       0
Bank Sta=0,28.255
XS Rating Curve= 0 ,0
Exp/Cntr=0.3,0.1

Type RM Length L Ch R = 1 ,6       ,25,25,25
XS GIS Cut Line= 6
789566.9970298243139529.68740967789566.7190365823139531.96695425
789568.3058767893139537.62272529789570.0773535513139541.16567882
789572.8408573013139550.73165334789574.8249112753139554.13288872
#Sta/Elev= 14
       01245.133    .5891244.359   2.6721243.897   3.9631242.998   5.6161242.324
   7.448 1242.53   9.5451242.499   11.531242.923   14.85 1243.56   17.16 1243.85
   24.58 1243.94   26.76 1243.62   30.07 1243.75  33.7341244.886
#Mann= 3 ,0,0
       0     .05       0       0    .038       0  33.734     .05       0
Bank Sta=0,33.734
XS Rating Curve= 0 ,0
Exp/Cntr=0.3,0.1

Type RM Length L Ch R = 1 ,5       ,25,25,25
XS GIS Cut Line= 6
     789587.0866     3139524.846     789589.5473     3139532.292
     789591.2319     3139532.194 789599.342145723139545.69502577
789598.9022763773139549.70883352789597.6376520163139549.65384985
#Sta/Elev= 17
       01245.641   1.4791243.999   3.7361242.153   5.1281241.841   6.2811241.784
   7.9011241.853   9.5881241.709  10.571 1241.82  12.8281242.056  15.4271241.888
  17.4691242.179   22.55 1242.77   27.09 1243.27   30.66 1242.42   35.38 1242.85
   38.68 1243.92  45.9761244.545
#Mann= 3 ,0,0
       0     .05       0       0    .038       0  45.976     .05       0
Bank Sta=0,45.976
XS Rating Curve= 0 ,0
Exp/Cntr=0.3,0.1

Type RM Length L Ch R = 1 ,4.6     ,50,50,50
XS GIS Cut Line= 6
789601.6486928573139516.89984828789602.1297066833139517.83655942
789602.5929692283139518.61910332789606.4841476413139525.86189537
 789610.281625223139533.02646973789611.5980841143139535.35558932
#Sta/Elev= 17
       01244.817    3.03 1244.22    4.01 1243.25     4.9 1242.72     5.7 1242.07
    6.68  1241.6    7.75 1241.03    8.73 1240.75   10.25 1240.62   12.48  1240.5
   14.17  1240.7   17.02 1240.75   20.05 1241.35   23.08 1242.22   25.31 1243.75
   34.22  1244.7  46.796 1245.57
#Mann= 3 ,0,0
       0     .05       0       0    .038       0  46.796     .05       0
Bank Sta=0,46.796
XS Rating Curve= 0 ,0
Exp/Cntr=0.3,0.1

Type RM Length L Ch R = 3 ,4.55    ,,,
Bridge Culvert--1,0,-1,-1, 0
Deck Dist Width WeirC Skew NumUp NumDn MinLoCord MaxHiCord MaxSubmerge Is_Ogee
,,1.4,0, 0, 0, , , 0.98, 0, 0,0,,
BR Coef=-1 , 0 , 0 ,, 0 ,,,0.8,-1,,0,
WSPro=,,,, 1 ,,,, 0 ,,,, 0 ,,,,-1 ,-1 ,-1 , 0 , 0 , 0 , 0 , 0
BC Design=,, 0 ,, 0 ,,,,,,
BC Use User HTab Curves=0
BC User HTab FreeFlow(D)= 0