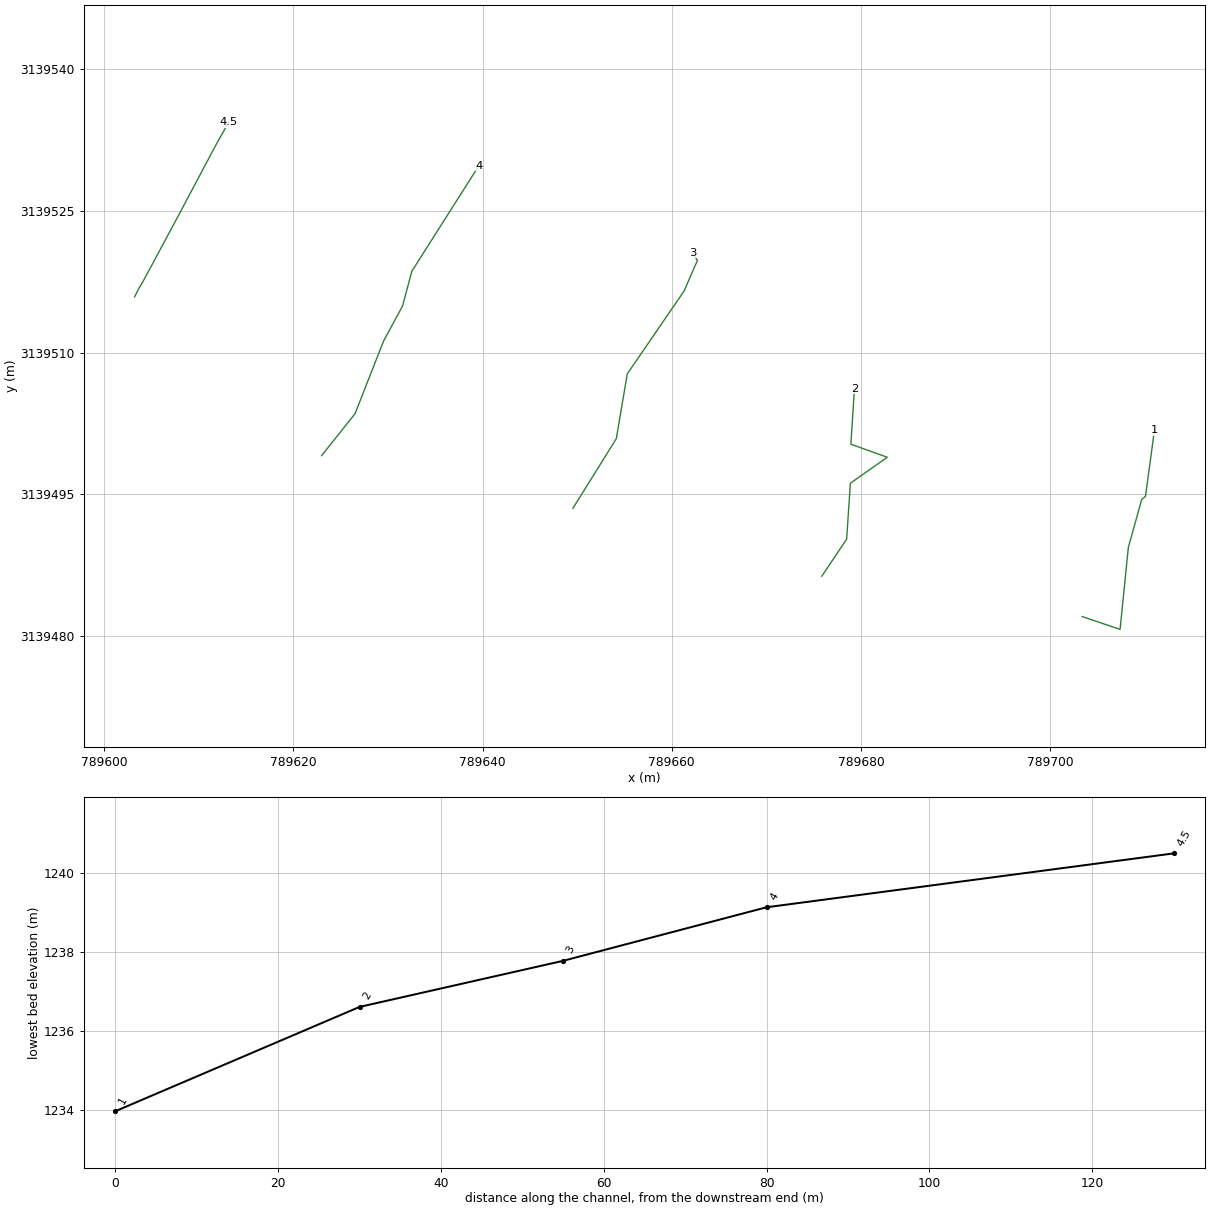
HEC-RAS study RiverDhiprangMode.prj: River Dhiprang Model

--- RiverDhiprangMode.g02 (geometry) --- (continued)

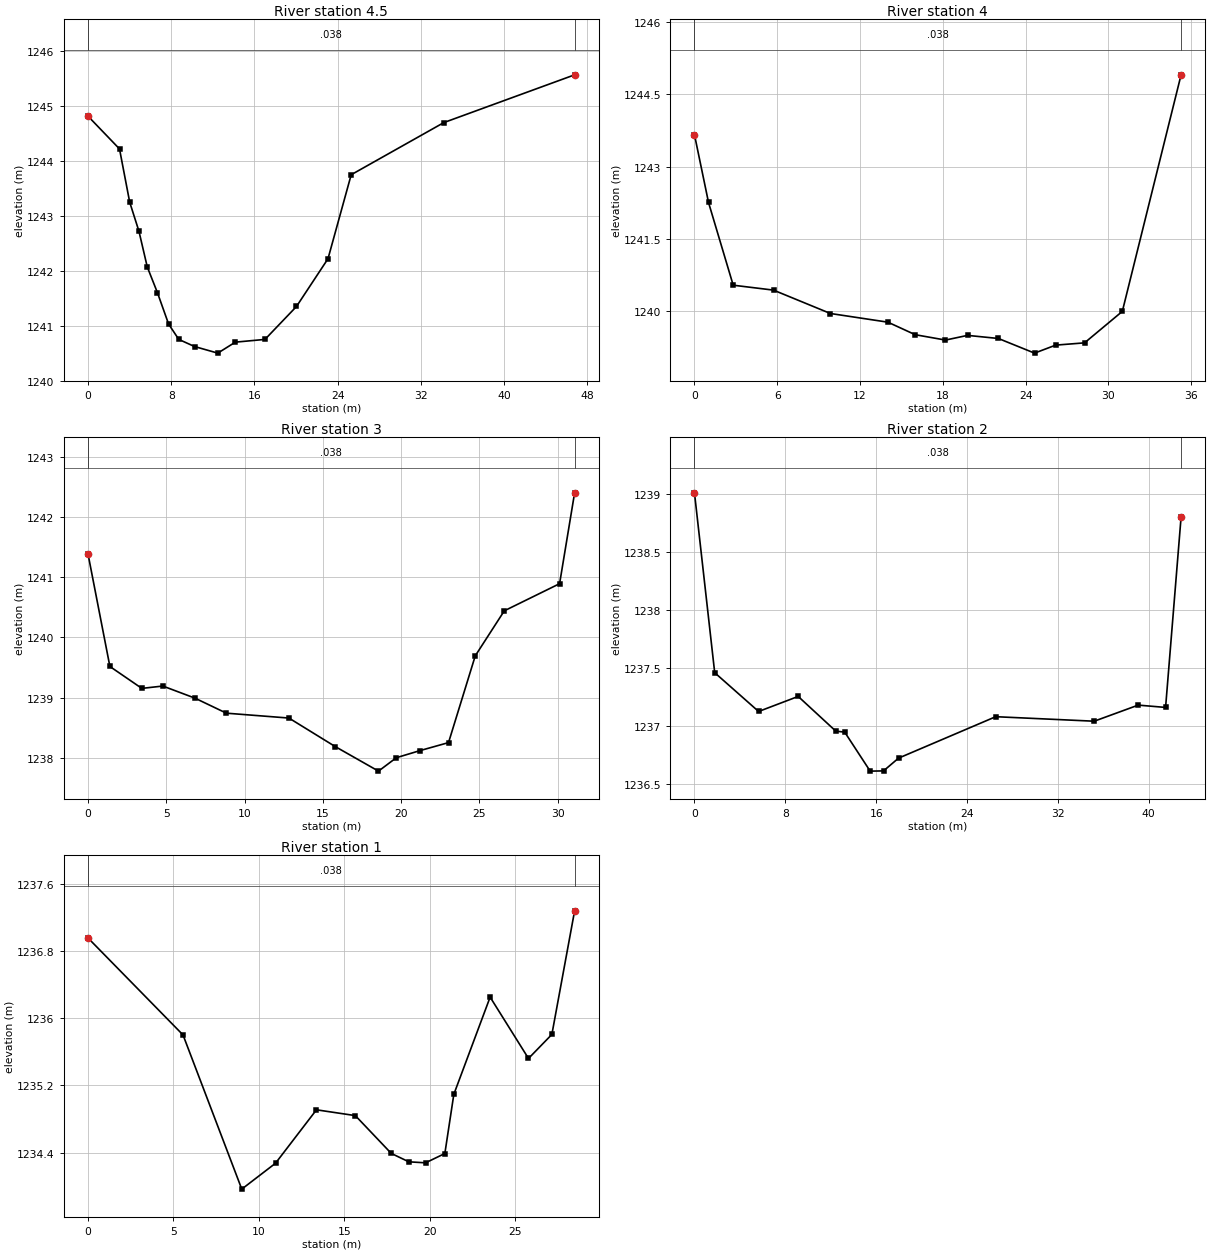
Type RM Length L Ch R = 1 ,4.5     ,50,50,50
XS GIS Cut Line= 6
789603.2010949763139515.88640114789603.6821088033139516.82311228
789604.1453713483139517.60565618 789608.036549763139524.84844823
 789611.834027343139532.01302259789613.1504862343139534.34214218
#Sta/Elev= 17
       01244.817    3.03 1244.22    4.01 1243.25     4.9 1242.72     5.7 1242.07
    6.68  1241.6    7.75 1241.03    8.73 1240.75   10.25 1240.62   12.48  1240.5
   14.17  1240.7   17.02 1240.75   20.05 1241.35   23.08 1242.22   25.31 1243.75
   34.22  1244.7  46.796 1245.57
#Mann= 3 ,0,0
       0     .05       0       0    .038       0  46.796     .05       0
Bank Sta=0,46.796
XS Rating Curve= 0 ,0
Exp/Cntr=0.3,0.1

Type RM Length L Ch R = 1 ,4       ,25,25,25
XS GIS Cut Line= 6
     789622.9774     3139499.105     789626.5074     3139503.533
      789629.539     3139511.244     789631.5301     3139514.912
     789632.5216     3139518.613     789639.6194     3139529.779
#Sta/Elev= 15
       01243.666   1.019 1242.26   2.8071240.544   5.7281240.442   9.8541239.957
  14.0191239.777      161239.517  18.1931239.406  19.7911239.503  22.0251239.439
  24.6471239.135  26.1781239.301  28.2711239.348  31.0091240.001  35.2671244.908
#Mann= 3 ,0,0
       0     .05       0       0    .038       0  35.267     .05       0
Bank Sta=0,35.267
XS Rating Curve= 0 ,0
Exp/Cntr=0.3,0.1

Type RM Length L Ch R = 1 ,3       ,25,25,25
XS GIS Cut Line= 6
     789649.5466     3139493.536     789654.1368      3139500.91
     789655.2929     3139507.744     789661.3001     3139516.514
     789662.7122      3139519.75     789662.1709     3139520.543
#Sta/Elev= 16
       01241.387   1.3981239.516   3.4391239.152   4.7791239.191    6.83 1238.99
   8.839 1238.74  12.8331238.659  15.7831238.186  18.5511237.777  19.692    1238
  21.2141238.119  23.0241238.251  24.7321239.693  26.5861240.441  30.1171240.892
  31.0771242.402
#Mann= 3 ,0,0
       0     .05       0       0    .038       0  31.077     .05       0
Bank Sta=0,31.077
XS Rating Curve= 0 ,0
Exp/Cntr=0.3,0.1

Type RM Length L Ch R = 1 ,2       ,30,30,30
XS GIS Cut Line= 6
     789675.8572      3139486.36789678.4840898013139490.27002827
     789678.8789     3139496.189789682.7789002753139498.93566356
     789678.9313     3139500.317     789679.3117     3139506.199
#Sta/Elev= 14
       01239.012   1.7821237.459   5.6491237.124   9.1331237.254  12.4491236.954
  13.2291236.946  15.4721236.609  16.6481236.611  17.9671236.721  26.5281237.079
    35.2 1237.04  39.0751237.179  41.4851237.159   42.851238.803
#Mann= 3 ,0,0
       0     .05       0       0    .038       0   42.85     .05       0
Bank Sta=0,42.85
XS Rating Curve= 0 ,0
Exp/Cntr=0.3,0.1

Type RM Length L Ch R = 1 ,1       ,0,0,0
XS GIS Cut Line= 6
789703.3782017773139482.09599964     789707.3919      3139480.74
     789708.2682     3139489.416     789709.6778     3139494.462
     789710.0779     3139494.802     789711.0226     3139501.786
#Sta/Elev= 15
       01236.954    5.56  1235.8   8.9981233.965  10.9721234.273  13.3681234.909
  15.642 1234.84  17.746 1234.39  18.773 1234.29  19.7521234.278  20.8811234.389
  21.4061235.093   23.53 1236.25  25.775 1235.52  27.1431235.806  28.4741237.277
#Mann= 3 ,0,0
       0     .05       0       0    .038       0  28.474     .05       0
Bank Sta=0,28.474
XS Rating Curve= 0 ,0
Exp/Cntr=0.3,0.1
LCMann Table=0